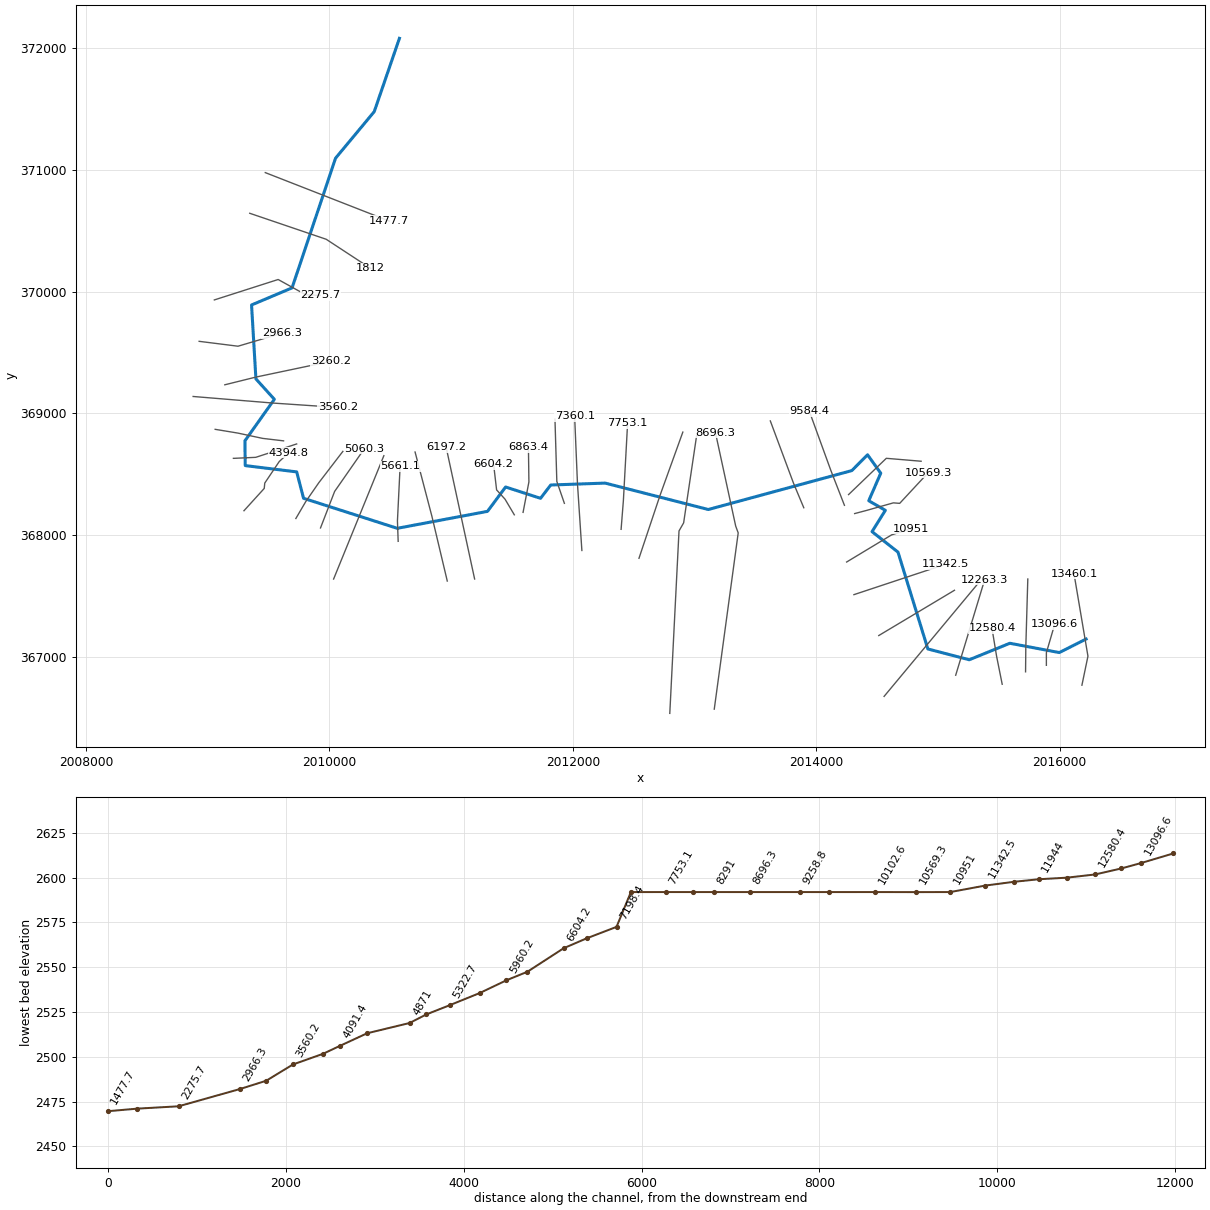
--- NP101.prj (project) ---

Proj Title=NP101
Current Plan=p01
Geom File=g01
Flow File=f01
Plan File=p01
DSS Export Rating Curves=0
DSS Export Rating Curve Sorted=0
DSS Export Volume Flow Curves=0
DXF OffsetX=0
DXF OffsetY=0
DXF ScaleX=0
DXF ScaleY=0

--- NP101.p01 (plan) ---

Plan Title=Floodplain
Program Version=4.00
Geom File=g01
Flow File=f01
K Sum by GR=0
Std Step Tol=0.01
Critical Tol=0.01
Num of Std Step Trials=20
Max Error Tol=0.3
Flow Tol Ratio=0.001
Split Flow NTrial=30
Split Flow Tol=0.02
Split Flow Ratio=0.02
Log Output Level=0
Friction Slope Method=1
Unsteady Friction Slope Method=2
Unsteady Bridges Friction Slope Method=1
Global Log Level=0
CheckData=False
Run HTab=0
Run UNet=0
Run PostProcess=0
UNET Theta=0
UNET Theta Warmup=0
UNET ZTol=0
UNET ZSATol=0
UNET MxIter=0
UNET MaxInSteps=0
UNET DtIC=0
UNET DtMin=0
UNET MaxCRTS=0
UNET WFStab=0
UNET SFStab=0
UNET WFX=0
UNET SFX=0
UNET DSS MLevel=0
UNET DZMax Abort=0
UNET Convert EG Bridges=0
UNET Use Existing IB Tables=0
UNET Froude Limit=0
UNET Froude Power=0
Write IC File=0
Echo Input=False
Echo Output=False
Write Detailed=0

--- NP101.f01 (steady flow) ---

Flow Title=NFF Regression Equation
Program Version=4.00
Number of Profiles=1
Profile Names=P100yr
River Rch & RM=NP101,Main      ,13460.1
513.8985
River Rch & RM=NP101,Main      ,11342.5
552.8357
River Rch & RM=NP101,Main      ,8291
611.8722
River Rch & RM=NP101,Main      ,8058.8
741.1990
River Rch & RM=NP101,Main      ,6197.2
764.4924
River Rch & RM=NP101,Main      ,4091.4
843.4826
River Rch & RM=NP101,Main      ,260.2
936.4221
Boundary for River Rch & Prof#=NP101,Main      ,1
Up Type=0
Dn Type=3
Dn Slope=0.004257

--- NP101.g01 (geometry) ---

Geom Title=USGS 3m DEM
Program Version=4.00

River Reach=NP101     ,Main
Reach XY= 30
     2016216.883      367145.539     2015996.397      367034.428
     2015590.147      367110.817     2015256.814      366975.401
     2014916.536      367063.942     2014671.152      367859.754
     2014457.853      368027.867     2014567.164      368203.151
     2014430.957      368281.832     2014529.383      368508.387
     2014421.117      368659.321     2014291.754      368529.439
     2013112.717      368209.775     2012265.494      368426.789
     2011817.871      368411.164     2011734.244      368301.789
     2011447.148      368394.861     2011298.471      368194.644
     2010557.161      368055.262     2009787.100      368301.878
     2009730.772      368518.803     2009307.816      368570.607
     2009305.425      368774.012     2009547.289      369115.403
     2009395.703      369282.692     2009359.876      369890.336
     2009692.631      370030.757     2010050.004      371096.229
     2010367.925      371478.873     2010574.755      372081.070

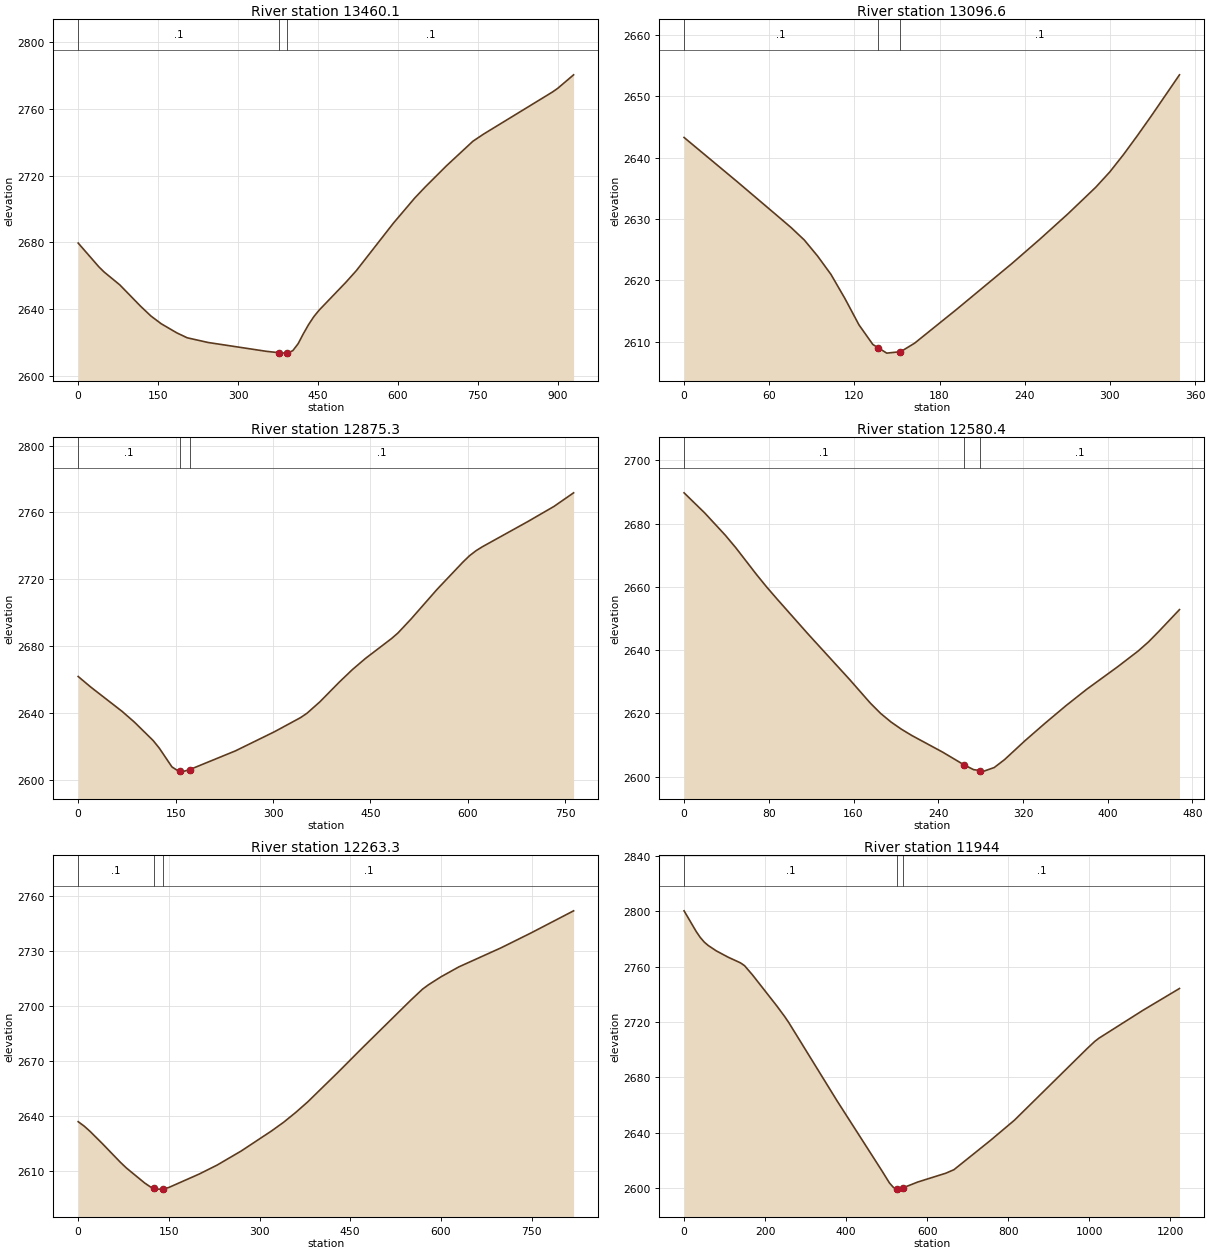
Type RM Length L Ch R = 1 ,13460.1,374.1,363.4,351.1
XS GIS Cut Line= 3
     2016182.332      366766.227     2016231.840      367004.764
     2016117.456      367681.282
#Sta/Elev= 30
       0 2679.49    39.0 2665.18    48.7 2662.13    78.0 2654.45   116.9 2641.69
   136.4 2635.78   155.9 2631.09   185.2 2625.62   204.6 2622.69   243.6 2619.88
   353.0 2614.58   377.4 2613.72   392.4 2613.49   402.7 2614.96   412.7 2619.11
   422.6 2625.13   432.6 2630.73   442.5 2635.48   452.4 2639.34   502.2 2655.91
   522.0 2662.96   591.6 2691.45   631.4 2706.44   651.3 2713.14   691.1 2725.82
   740.8 2740.56   760.7 2744.82   890.0 2770.06   899.9 2772.27   929.7 2780.38
#Mann= 3 , 0 , 0
       0     0.1       0   377.4   0.045       0   392.4     0.1       0
Bank Sta=   377.4,   392.4
Exp/Cntr=0.3,0.1

Type RM Length L Ch R = 1 ,13096.6,214.4,221.1,227.3
XS GIS Cut Line= 3
     2015890.287      366929.753     2015890.287      367033.269
     2015959.298      367268.805
#Sta/Elev= 25
       0 2643.31    37.6 2636.06    65.9 2630.49    75.3 2628.63    84.7 2626.58
    94.1 2623.95   103.5 2620.96   113.3 2617.04   123.2 2612.74   133.0 2609.53
   136.8 2608.98   142.8 2608.12   151.8 2608.34   152.6 2608.36   162.4 2609.74
   191.9 2615.24   231.1 2622.77   250.8 2626.74   270.4 2630.84   290.0 2635.18
   299.9 2637.68   309.7 2640.56   319.5 2643.66   329.3 2646.87   349.0 2653.53
#Mann= 3 , 0 , 0
       0     0.1       0   136.8   0.045       0   151.8     0.1       0
Bank Sta=   136.8,   151.8
Exp/Cntr=0.3,0.1

Type RM Length L Ch R = 1 ,12875.3,291.2,294.2,297.3
XS GIS Cut Line= 3
     2015719.316      366876.189     2015721.316      367078.220
     2015737.692      367638.820
#Sta/Elev= 30
       0 2661.78    19.2 2655.50    67.4 2640.96    86.6 2634.45   115.4 2623.45
   125.1 2618.78   144.3 2607.68   153.9 2605.21   156.8 2605.18   163.6 2605.11
   171.8 2606.04   242.1 2617.23   302.2 2628.68   342.2 2637.10   352.3 2639.75
   372.3 2646.65   402.3 2658.50   422.4 2665.96   442.4 2672.60   482.5 2684.49
   492.5 2687.86   512.5 2696.16   552.6 2713.93   592.6 2730.34   602.6 2734.09
   612.7 2737.12   622.7 2739.53   692.8 2754.64   732.8 2763.65   762.9 2771.77
#Mann= 3 , 0 , 0
       0     0.1       0   156.8   0.045       0   171.8     0.1       0
Bank Sta=   156.8,   171.8
Exp/Cntr=0.3,0.1

Type RM Length L Ch R = 1 ,12580.4,327.1,317.3,307.5
XS GIS Cut Line= 3
     2015527.286      366774.173     2015481.279      367004.208
     2015443.273      367234.244
#Sta/Elev= 30
       0 2689.74    19.6 2683.35    39.1 2676.28    48.9 2672.36    68.4 2663.92
    78.2 2659.89    88.0 2656.10   117.3 2645.03   156.4 2630.70   175.9 2623.26
   185.7 2619.98   195.5 2617.27   205.3 2615.00   215.0 2613.04   244.3 2607.74
   264.5 2603.72   273.4 2602.23   279.5 2601.94   283.2 2601.76   292.9 2602.90
   302.6 2605.39   322.0 2611.40   341.4 2617.05   360.9 2622.53   380.3 2627.66
   409.5 2634.77   428.9 2639.76   438.6 2642.63   448.3 2645.93   467.8 2652.82
#Mann= 3 , 0 , 0
       0     0.1       0   264.5   0.045       0   279.5     0.1       0
Bank Sta=   264.5,   279.5
Exp/Cntr=0.3,0.1

Type RM Length L Ch R = 1 ,12263.3,328.1,319.3,310.4
XS GIS Cut Line= 2
     2015145.227      366848.184     2015383.100      367632.435
#Sta/Elev= 30
       0 2636.72    10.0 2634.29    20.0 2631.33    40.0 2624.77    70.0 2614.53
    80.0 2611.41   109.9 2603.32   119.9 2601.08   125.4 2600.47   129.9 2599.97
   139.9 2599.96   140.4 2600.00   149.9 2600.86   199.9 2608.14   229.9 2613.08
   269.8 2620.77   319.8 2631.66   339.8 2636.40   359.8 2641.74   379.8 2647.54
   429.8 2663.63   469.7 2676.83   549.7 2702.79   569.7 2708.98   579.7 2711.40
   599.7 2715.60   629.6 2721.08   699.6 2731.50   749.6 2739.68   819.5 2751.65
#Mann= 3 , 0 , 0
       0     0.1       0   125.4   0.045       0   140.4     0.1       0
Bank Sta=   125.4,   140.4
Exp/Cntr=0.3,0.1

Type RM Length L Ch R = 1 ,11944,285,277.4,269.8
XS GIS Cut Line= 2
     2014557.036      366674.371     2015338.981      367614.289
#Sta/Elev= 30
       0 2800.45    29.8 2785.58    39.8 2781.25    49.7 2777.87    59.6 2775.37
    79.5 2771.48   109.3 2766.83   139.2 2762.80   149.1 2760.82   169.0 2754.03
   228.6 2731.75   248.5 2723.87   258.4 2719.59   377.7 2662.91   487.1 2612.88
   507.0 2603.49   516.9 2600.25   525.5 2599.22   526.8 2599.07   540.5 2600.01
   576.5 2604.19   646.1 2610.60   666.0 2613.13   755.5 2634.17   815.1 2648.90
   994.0 2700.58  1013.9 2706.05  1023.8 2708.28  1133.2 2728.60  1222.6 2744.24
#Mann= 3 , 0 , 0
       0     0.1       0   525.5   0.045       0   540.5     0.1       0
Bank Sta=   525.5,   540.5
Exp/Cntr=0.3,0.1

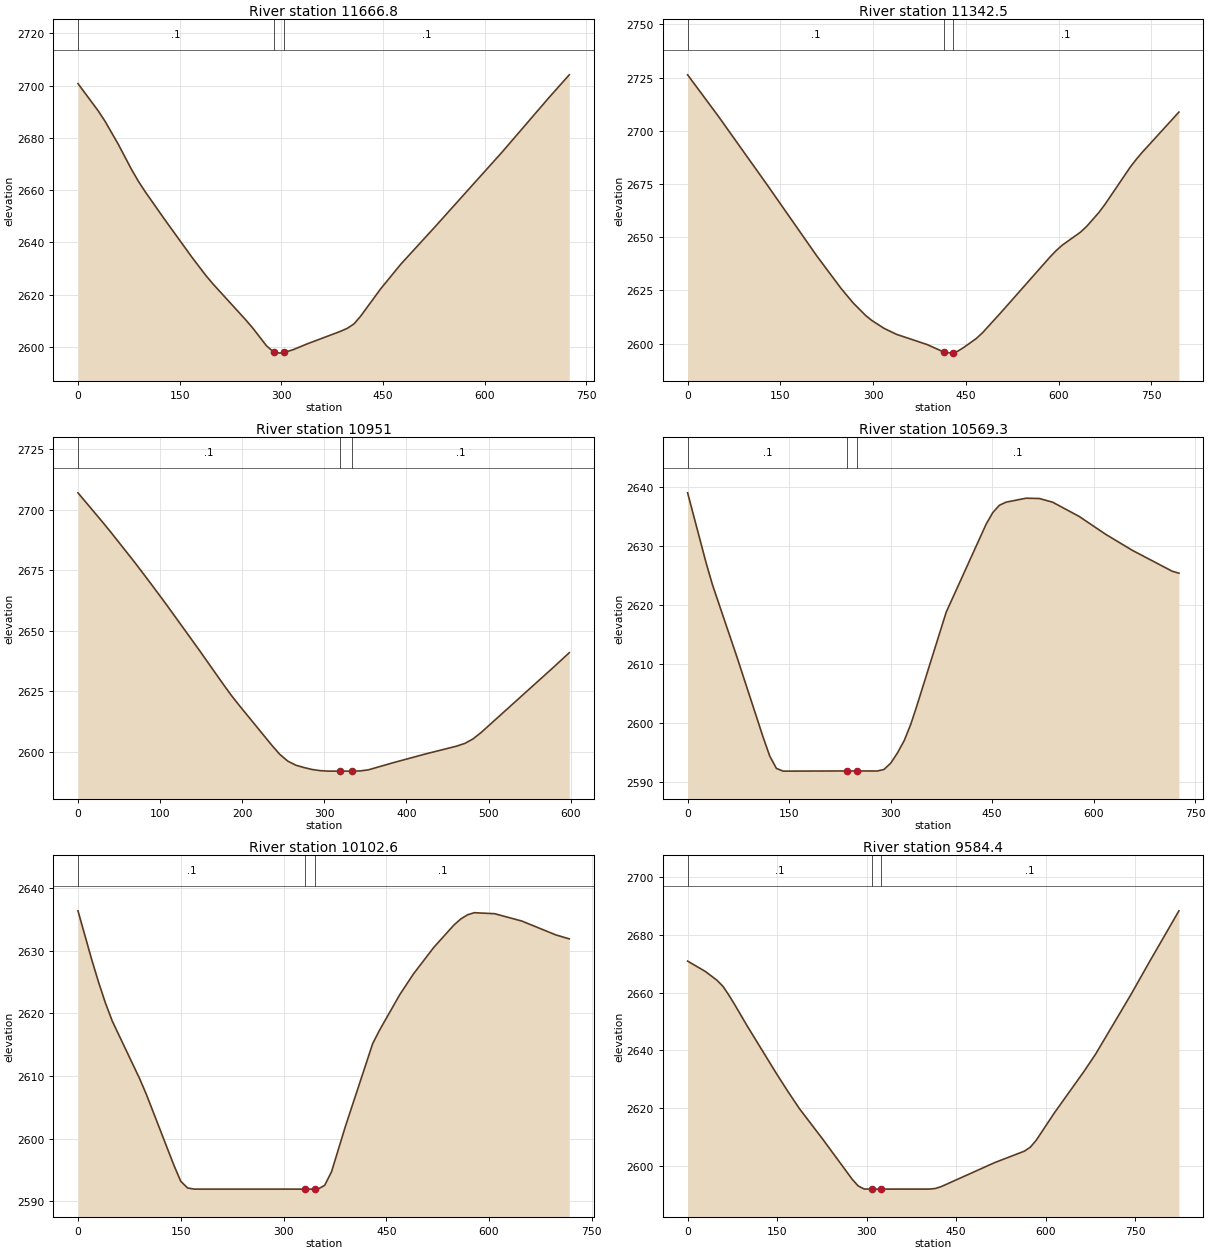
Type RM Length L Ch R = 1 ,11666.8,329,324.1,319.1
XS GIS Cut Line= 2
     2014513.130      367174.235     2015135.226      367546.292
#Sta/Elev= 30
       0 2700.73    29.8 2690.33    39.7 2686.44    59.6 2677.47    79.4 2667.72
    89.4 2663.27    99.3 2659.34   129.1 2648.34   168.8 2634.10   188.7 2627.34
   198.6 2624.29   248.2 2610.18   258.2 2607.14   278.0 2600.50   288.0 2598.22
   289.5 2598.13   297.9 2597.65   304.5 2597.91   317.8 2598.99   337.6 2601.13
   387.3 2605.98   397.2 2607.11   407.1 2608.79   417.0 2611.76   446.8 2622.31
   476.6 2631.74   526.3 2645.82   625.6 2674.48   695.1 2695.43   724.9 2704.09
#Mann= 3 , 0 , 0
       0     0.1       0   289.5   0.045       0   304.5     0.1       0
Bank Sta=   289.5,   304.5
Exp/Cntr=0.3,0.1

Type RM Length L Ch R = 1 ,11342.5,386.7,391.5,395.4
XS GIS Cut Line= 2
     2014309.098      367510.287     2015063.215      367760.325
#Sta/Elev= 30
       0 2726.33    49.7 2706.86   129.1 2674.43   208.6 2641.34   248.3 2625.88
   268.1 2619.00   288.0 2613.20   297.9 2610.87   317.8 2607.16   337.7 2604.37
   387.3 2599.56   414.3 2596.04   427.0 2595.53   429.3 2595.74   437.0 2596.46
   446.9 2598.26   466.8 2602.40   476.7 2605.04   506.5 2614.55   585.9 2640.67
   595.9 2643.68   605.8 2646.27   635.6 2652.44   645.5 2655.14   665.4 2661.74
   675.3 2665.60   715.0 2682.62   725.0 2686.42   734.9 2689.82   794.5 2708.82
#Mann= 3 , 0 , 0
       0     0.1       0   414.3   0.045       0   429.3     0.1       0
Bank Sta=   414.3,   429.3
Exp/Cntr=0.3,0.1

Type RM Length L Ch R = 1 ,10951,384.1,381.4,377.7
XS GIS Cut Line= 3
     2014249.089      367778.328     2014619.175      368001.629
     2014777.170      368052.371
#Sta/Elev= 30
       0 2706.95    29.5 2695.04    39.3 2690.98    68.8 2678.34    88.4 2669.58
   108.1 2660.57   147.4 2642.07   176.8 2627.89   186.6 2623.30   196.5 2619.04
   235.8 2602.72   245.6 2598.90   255.4 2596.08   265.2 2594.39   275.1 2593.42
   284.9 2592.62   294.7 2592.14   304.5 2591.93   319.1 2591.93   334.1 2591.94
   343.8 2592.02   353.6 2592.46   383.1 2595.34   422.4 2598.96   461.5 2602.30
   471.3 2603.43   481.0 2605.24   490.8 2607.87   578.7 2634.77   598.2 2640.87
#Mann= 3 , 0 , 0
       0     0.1       0   319.1   0.045       0   334.1     0.1       0
Bank Sta=   319.1,   334.1
Exp/Cntr=0.3,0.1

Type RM Length L Ch R = 1 ,10569.3,456.7,466.3,474.6
XS GIS Cut Line= 5
     2014315.099      368176.390     2014413.114      368202.394
     2014633.148      368264.403     2014685.156      368260.403
     2014919.192      368512.442
#Sta/Elev= 30
       0 2638.94    27.7 2626.94    36.9 2623.34    73.8 2610.88   111.4 2597.70
   121.3 2594.47   131.2 2592.36   141.2 2591.90   235.6 2591.93   250.6 2591.93
   280.3 2591.92   290.2 2592.18   300.2 2593.25   310.1 2594.97   320.1 2597.06
   330.0 2599.88   338.7 2602.91   382.2 2618.78   441.1 2633.62   451.0 2635.60
   460.8 2636.84   470.6 2637.36   500.1 2638.03   519.8 2637.98   539.4 2637.36
   578.7 2634.95   618.0 2631.92   657.3 2629.22   716.3 2625.68   726.1 2625.36
#Mann= 3 , 0 , 0
       0     0.1       0   235.6   0.045       0   250.6     0.1       0
Bank Sta=   235.6,   250.6
Exp/Cntr=0.3,0.1

Type RM Length L Ch R = 1 ,10102.6,490.7,517.9,543.6
XS GIS Cut Line= 3
     2014265.091      368332.414     2014575.139      368630.460
     2014861.183      368606.456
#Sta/Elev= 30
       0 2636.39    20.0 2628.62    30.0 2625.01    40.0 2621.69    50.0 2618.79
    90.0 2609.58   100.0 2607.02   140.0 2595.75   150.0 2593.19   160.0 2592.11
   170.0 2591.93   331.6 2591.93   346.6 2591.93   350.1 2591.93   360.1 2592.54
   370.1 2594.71   390.1 2601.87   430.1 2615.16   440.0 2617.29   469.7 2623.00
   489.5 2626.28   519.2 2630.53   548.8 2634.13   558.8 2635.09   568.6 2635.76
   578.6 2636.09   608.2 2635.93   647.8 2634.76   697.3 2632.55   717.1 2631.91
#Mann= 3 , 0 , 0
       0     0.1       0   331.6   0.045       0   346.6     0.1       0
Bank Sta=   331.6,   346.6
Exp/Cntr=0.3,0.1

Type RM Length L Ch R = 1 ,9584.4,324.8,325.6,325.7
XS GIS Cut Line= 3
     2014231.086      368244.400     2014120.106      368529.193
     2013943.088      369015.991
#Sta/Elev= 30
       0 2670.99    29.6 2667.41    49.3 2664.34    59.2 2662.24    69.0 2659.25
    78.9 2655.91    98.6 2648.94   147.9 2632.32   167.6 2625.96   187.3 2619.87
   226.8 2609.16   276.1 2595.28   285.9 2593.04   295.8 2591.97   305.6 2591.92
   309.6 2591.92   324.6 2591.93   405.3 2591.93   415.2 2592.14   425.2 2592.80
   514.8 2601.12   564.6 2605.09   574.6 2606.48   584.6 2608.92   614.4 2618.23
   664.3 2632.68   684.2 2638.82   744.0 2659.67   773.8 2670.59   823.6 2688.42
#Mann= 3 , 0 , 0
       0     0.1       0   309.6   0.045       0   324.6     0.1       0
Bank Sta=   309.6,   324.6
Exp/Cntr=0.3,0.1

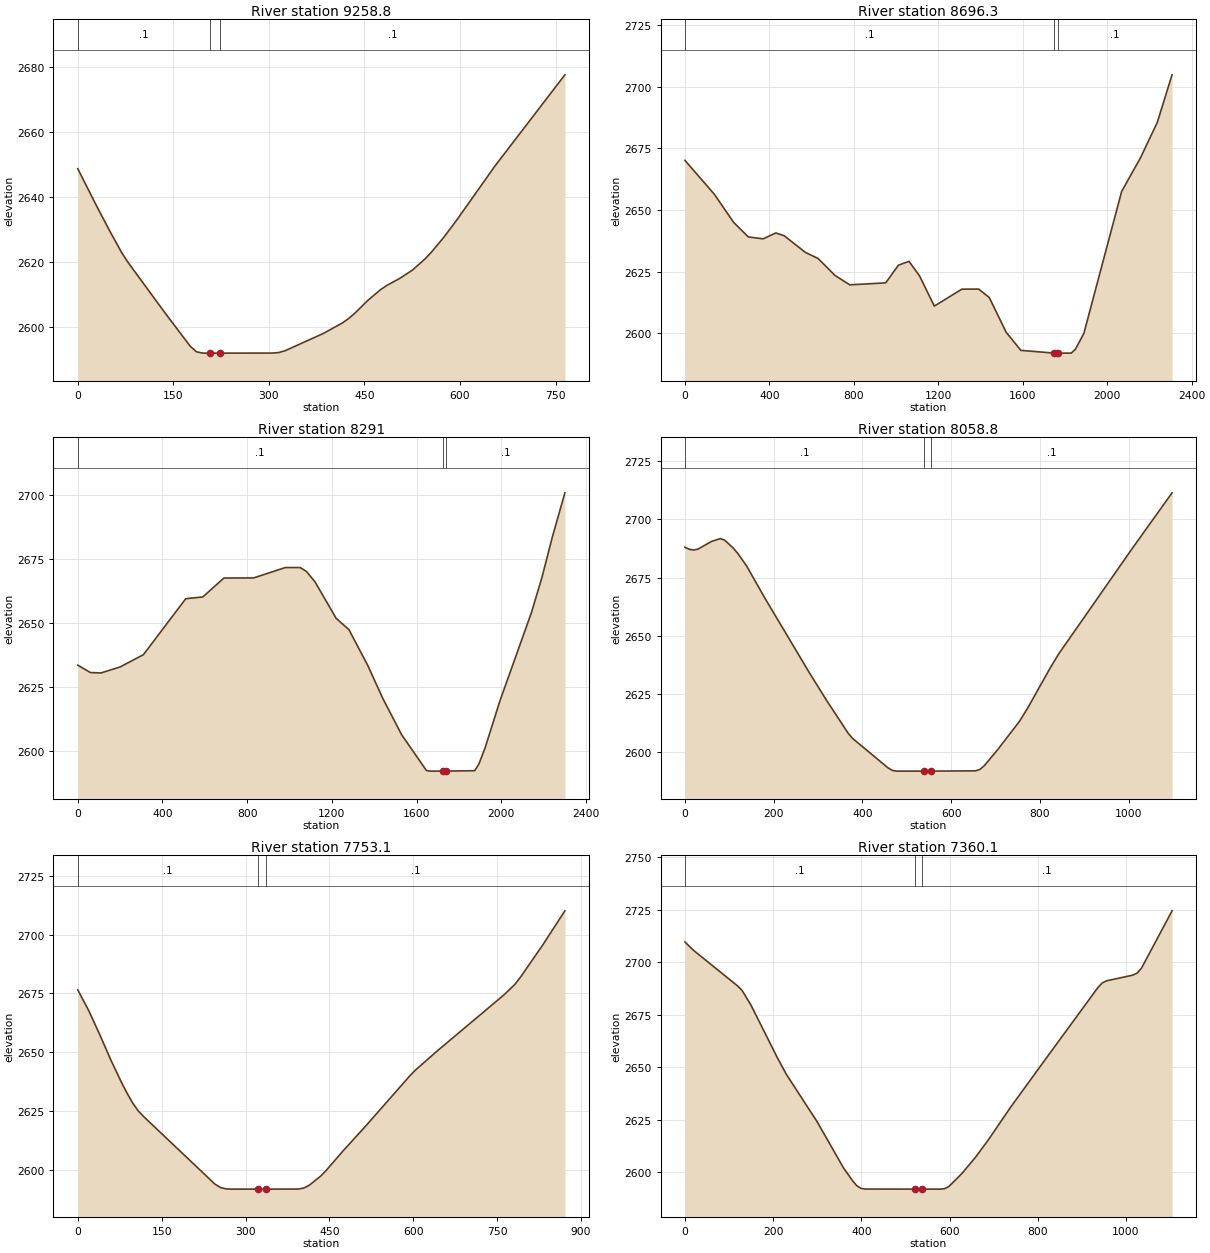
Type RM Length L Ch R = 1 ,9258.8,566.2,562,558.8
XS GIS Cut Line= 3
     2013897.034      368224.397     2013813.666      368423.373
     2013622.182      368937.784
#Sta/Elev= 30
       0 2648.62    29.4 2637.24    49.0 2629.91    68.6 2622.94    78.4 2619.96
   137.3 2604.21   176.5 2594.07   186.3 2592.34   196.1 2591.94   205.9 2591.93
   208.2 2591.93   223.2 2591.93   305.6 2591.95   315.5 2592.11   325.5 2592.67
   385.4 2597.97   415.3 2601.20   425.3 2602.59   435.3 2604.28   455.2 2608.13
   475.2 2611.44   485.2 2612.75   505.2 2614.88   525.1 2617.43   545.1 2620.89
   555.0 2622.95   575.0 2627.65   595.0 2632.88   654.8 2649.45   764.6 2677.49
#Mann= 3 , 0 , 0
       0     0.1       0   208.2   0.045       0   223.2     0.1       0
Bank Sta=   208.2,   223.2
Exp/Cntr=0.3,0.1

Type RM Length L Ch R = 1 ,8696.3,413.3,405.3,397.3
XS GIS Cut Line= 4
     2013161.587      366569.475     2013358.294      368017.457
     2013337.614      368073.707     2013171.236      368841.607
#Sta/Elev= 30
       0 2670.09   140.1 2656.25   230.2 2644.98   300.3 2639.03   370.3 2638.27
   430.4 2640.65   470.4 2639.50   570.5 2632.76   630.6 2630.30   710.6 2623.42
   780.7 2619.61   950.8 2620.41  1010.9 2627.58  1060.9 2629.14  1111.0 2623.25
  1181.0 2610.99  1311.2 2617.85  1391.2 2617.89  1441.3 2614.46  1521.2 2600.39
  1590.8 2593.04  1749.4 2591.93  1764.4 2591.93  1829.5 2591.92  1849.4 2593.52
  1889.2 2599.93  2068.2 2657.48  2157.7 2671.17  2237.3 2685.56  2306.9 2704.77
#Mann= 3 , 0 , 0
       0     0.1       0  1749.4   0.045       0  1764.4     0.1       0
Bank Sta=  1749.4,  1764.4
Exp/Cntr=0.3,0.1

Type RM Length L Ch R = 1 ,8291,236.2,232,227.3
XS GIS Cut Line= 4
     2012796.197      366534.803     2012871.896      368033.498
     2012909.953      368100.119     2013016.450      368815.362
#Sta/Elev= 30
       0 2633.41    60.0 2630.51   110.0 2630.37   200.1 2632.71   310.1 2637.52
   510.2 2659.44   590.2 2660.10   690.3 2667.52   830.3 2667.55   980.4 2671.62
  1050.4 2671.62  1080.4 2670.07  1120.4 2666.02  1220.5 2651.71  1280.5 2647.33
  1370.6 2633.13  1440.6 2620.38  1529.4 2606.20  1646.7 2592.16  1666.5 2591.93
  1722.8 2591.93  1737.8 2591.93  1874.5 2592.10  1894.3 2594.70  1924.0 2601.12
  1993.4 2619.36  2142.0 2653.86  2191.5 2667.55  2241.0 2683.48  2300.5 2700.87
#Mann= 3 , 0 , 0
       0     0.1       0  1722.8   0.045       0  1737.8     0.1       0
Bank Sta=  1722.8,  1737.8
Exp/Cntr=0.3,0.1

Type RM Length L Ch R = 1 ,8058.8,299.6,305.7,312.3
XS GIS Cut Line= 3
     2012543.038      367809.114     2012716.571      368327.621
     2012903.436      368845.925
#Sta/Elev= 30
       0 2688.06     9.9 2687.18    19.9 2686.86    29.8 2687.29    59.6 2690.54
    79.5 2691.77    89.5 2691.13   109.4 2687.60   119.3 2685.36   139.2 2679.97
   178.9 2666.62   278.4 2634.81   318.1 2622.62   367.8 2608.21   377.8 2605.97
   457.3 2593.39   467.2 2592.24   477.2 2591.93   539.3 2591.93   554.3 2591.93
   655.0 2592.06   664.8 2592.66   674.7 2594.29   704.2 2601.02   753.4 2613.19
   773.1 2619.24   822.3 2635.97   841.9 2642.17  1009.2 2687.86  1097.7 2711.43
#Mann= 3 , 0 , 0
       0     0.1       0   539.3   0.045       0   554.3     0.1       0
Bank Sta=   539.3,   554.3
Exp/Cntr=0.3,0.1

Type RM Length L Ch R = 1 ,7753.1,390.3,393,395.5
XS GIS Cut Line= 3
     2012396.136      368047.036     2012414.805      368281.739
     2012449.477      368916.504
#Sta/Elev= 30
       0 2676.51    19.6 2667.71    39.2 2657.56    58.9 2646.88    78.5 2637.06
    88.3 2632.60    98.1 2628.54   107.9 2625.19   117.7 2622.76   245.4 2594.04
   255.3 2592.60   265.2 2592.03   275.2 2591.93   321.6 2591.93   336.6 2591.93
   394.4 2591.96   404.3 2592.38   414.2 2593.62   434.1 2597.39   444.0 2599.78
   473.8 2607.98   513.6 2618.34   593.0 2639.78   603.0 2642.26   642.7 2650.54
   761.9 2674.31   781.8 2678.84   791.7 2681.87   831.4 2695.49   871.2 2710.05
#Mann= 3 , 0 , 0
       0     0.1       0   321.6   0.045       0   336.6     0.1       0
Bank Sta=   321.6,   336.6
Exp/Cntr=0.3,0.1

Type RM Length L Ch R = 1 ,7360.1,154.4,161.5,168.7
XS GIS Cut Line= 3
     2012073.853      367873.183     2012037.714      368421.298
     2012014.323      368975.855
#Sta/Elev= 30
       0 2709.71    20.0 2705.64   119.8 2688.70   129.8 2686.55   149.8 2679.58
   209.7 2654.49   229.7 2646.70   299.6 2624.08   359.6 2602.01   379.5 2596.06
   389.5 2593.57   399.5 2592.25   409.5 2591.95   522.5 2591.93   537.5 2591.93
   579.0 2591.92   589.0 2592.15   598.9 2593.26   628.6 2599.52   658.3 2606.98
   688.1 2615.46   737.6 2630.74   816.9 2653.69   935.9 2687.87   945.8 2690.16
   955.7 2691.19  1015.2 2693.90  1025.1 2694.85  1035.0 2697.19  1104.4 2724.56
#Mann= 3 , 0 , 0
       0     0.1       0   522.5   0.045       0   537.5     0.1       0
Bank Sta=   522.5,   537.5
Exp/Cntr=0.3,0.1

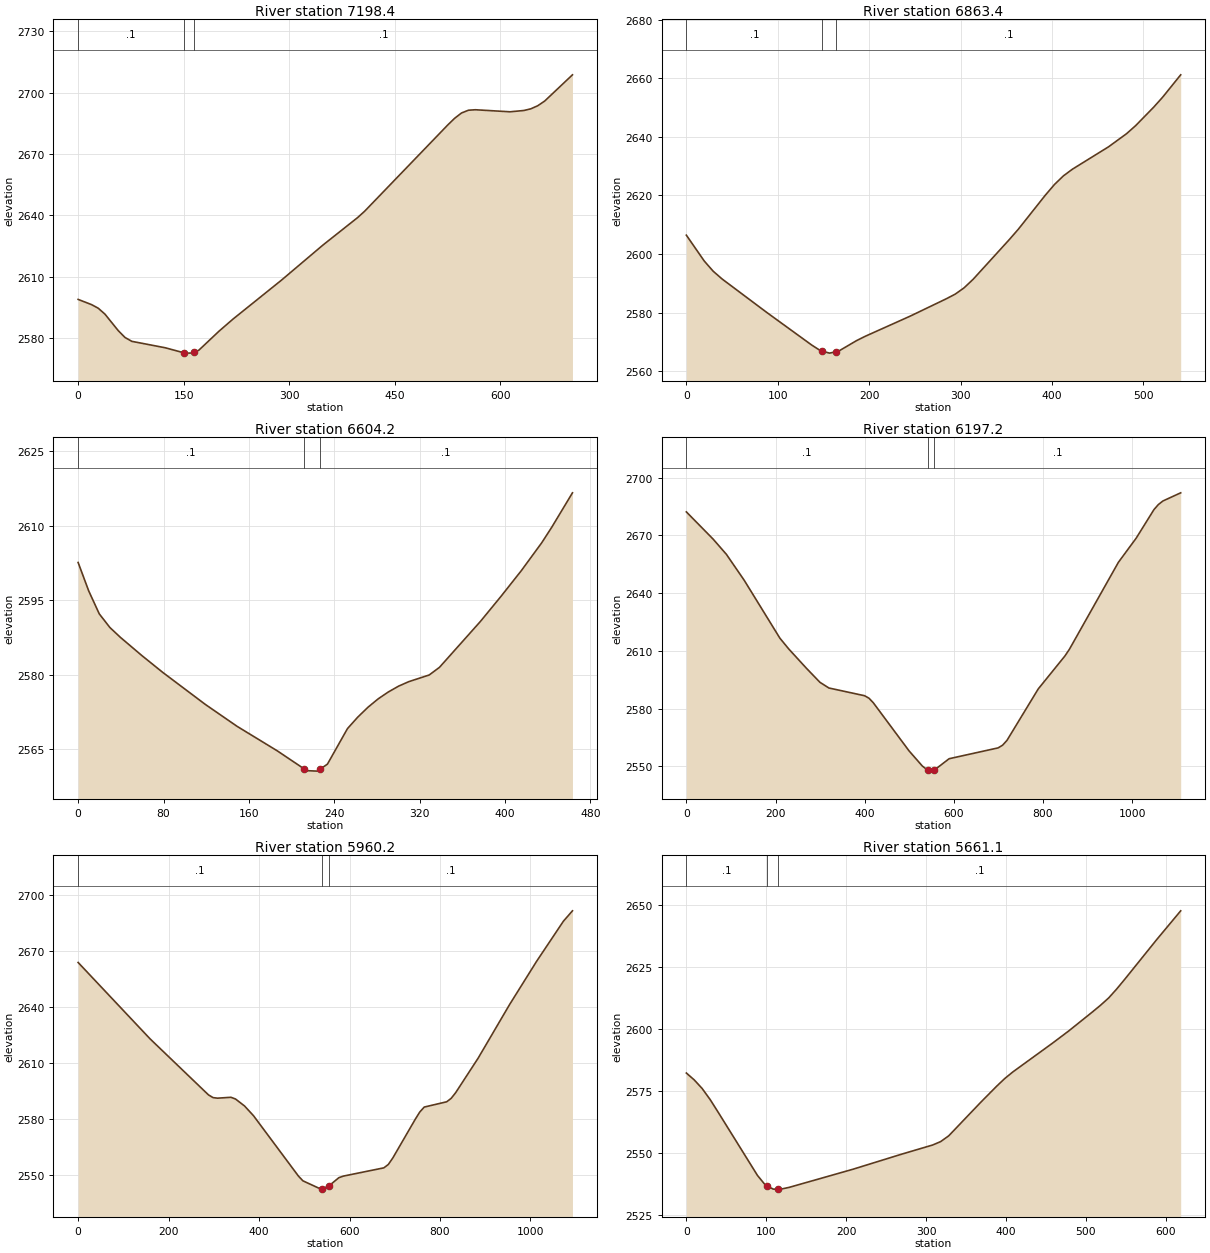
Type RM Length L Ch R = 1 ,7198.4,347.7,334.6,321.5
XS GIS Cut Line= 3
     2011930.096      368260.580     2011868.087      368440.608
     2011852.772      368952.318
#Sta/Elev= 30
       0 2598.80    19.0 2596.26    28.6 2594.48    38.1 2591.59    57.1 2583.48
    66.6 2580.17    76.2 2578.28   123.8 2575.12   149.9 2572.69   152.3 2572.50
   161.8 2572.53   164.9 2572.97   171.4 2573.89   200.2 2583.25   219.9 2589.12
   288.9 2608.22   347.9 2625.42   397.2 2638.88   407.0 2641.93   525.1 2684.16
   535.0 2687.47   544.8 2690.08   554.7 2691.43   564.5 2691.65   613.7 2690.65
   633.4 2691.29   643.3 2692.11   653.1 2693.62   663.0 2695.93   702.4 2708.75
#Mann= 3 , 0 , 0
       0     0.1       0   149.9   0.045       0   164.9     0.1       0
Bank Sta=   149.9,   164.9
Exp/Cntr=0.3,0.1

Type RM Length L Ch R = 1 ,6863.4,238.1,259.3,280.4
XS GIS Cut Line= 3
     2011590.678      368186.391     2011638.685      368436.430
     2011634.684      368722.474
#Sta/Elev= 30
       0 2606.42    19.6 2597.58    29.4 2594.09    39.2 2591.43    88.1 2580.00
   137.1 2568.90   146.9 2566.94   148.7 2566.79   156.7 2566.14   163.7 2566.62
   166.5 2566.81   186.1 2570.40   195.8 2571.91   244.8 2578.77   284.2 2584.68
   294.1 2586.29   303.9 2588.47   313.8 2591.40   353.2 2604.90   363.1 2608.45
   392.7 2620.10   402.6 2623.72   412.4 2626.67   422.3 2628.96   461.8 2636.60
   481.5 2641.08   491.4 2643.82   511.1 2650.11   521.0 2653.56   540.7 2661.18
#Mann= 3 , 0 , 0
       0     0.1       0   148.7   0.045       0   163.7     0.1       0
Bank Sta=   148.7,   163.7
Exp/Cntr=0.3,0.1

Type RM Length L Ch R = 1 ,6604.2,419,407,395.2
XS GIS Cut Line= 4
     2011518.666      368166.388     2011442.655      368294.408
     2011373.187      368371.100     2011348.640      368580.452
#Sta/Elev= 30
       0 2602.63     9.9 2596.91    19.8 2592.28    29.8 2589.52    39.7 2587.53
    59.6 2583.90    79.4 2580.47   119.1 2574.05   148.9 2569.63   186.5 2564.70
   211.4 2561.11   214.7 2560.69   224.1 2560.60   226.4 2560.94   233.6 2562.01
   252.4 2569.17   261.9 2571.45   271.5 2573.45   281.1 2575.15   290.7 2576.55
   300.3 2577.72   309.8 2578.62   329.0 2579.97   338.6 2581.51   376.9 2590.74
   396.1 2595.77   415.2 2600.96   434.4 2606.60   444.0 2609.80   463.2 2616.66
#Mann= 3 , 0 , 0
       0     0.1       0   211.4   0.045       0   226.4     0.1       0
Bank Sta=   211.4,   226.4
Exp/Cntr=0.3,0.1

Type RM Length L Ch R = 1 ,6197.2,236.3,236.7,237.6
XS GIS Cut Line= 2
     2011192.700      367638.647     2010958.403      368722.444
#Sta/Elev= 30
       0 2682.24    59.9 2668.12    89.9 2660.15   129.9 2646.65   209.8 2616.60
   229.8 2610.96   269.7 2600.87   299.7 2593.65   319.7 2590.71   399.6 2586.70
   409.6 2585.41   419.6 2582.95   499.5 2558.03   529.4 2550.12   541.3 2548.01
   549.4 2547.50   556.3 2548.07   589.4 2553.95   699.3 2559.58   709.2 2560.96
   719.2 2563.50   789.2 2590.20   849.1 2607.35   859.1 2610.80   969.0 2656.01
  1008.9 2668.57  1048.9 2683.46  1058.9 2686.09  1068.9 2687.91  1108.8 2692.15
#Mann= 3 , 0 , 0
       0     0.1       0   541.3   0.045       0   556.3     0.1       0
Bank Sta=   541.3,   556.3
Exp/Cntr=0.3,0.1

Type RM Length L Ch R = 1 ,5960.2,303.5,299,294
XS GIS Cut Line= 3
     2010967.972      367621.924     2010841.723      368153.812
     2010703.383      368682.127
#Sta/Elev= 30
       0 2663.88   159.0 2623.05   288.2 2593.07   298.2 2591.63   308.1 2591.33
   337.9 2591.80   347.9 2590.88   367.8 2587.17   387.6 2581.98   487.0 2549.68
   497.0 2547.13   536.7 2542.70   539.2 2542.81   554.2 2544.39   576.4 2548.82
   586.4 2549.67   675.8 2554.07   685.7 2555.88   695.6 2559.34   745.3 2580.06
   755.2 2583.90   765.1 2586.57   814.8 2589.40   824.7 2591.24   834.6 2594.27
   884.3 2612.72   953.8 2641.38  1013.4 2664.45  1072.9 2685.98  1092.8 2691.49
#Mann= 3 , 0 , 0
       0     0.1       0   539.2   0.045       0   554.2     0.1       0
Bank Sta=   539.2,   554.2
Exp/Cntr=0.3,0.1

Type RM Length L Ch R = 1 ,5661.1,348,338.4,328.9
XS GIS Cut Line= 3
     2010564.519      367948.354     2010558.518      368116.380
     2010580.521      368566.450
#Sta/Elev= 30
       0 2582.39     9.9 2579.60    19.8 2576.14    29.7 2571.73    39.6 2566.71
    89.0 2541.14    98.9 2537.25   100.3 2537.02   108.8 2535.62   115.3 2535.63
   118.7 2535.64   128.6 2536.32   208.2 2543.60   268.3 2549.59   308.3 2553.40
   318.3 2554.77   328.4 2557.10   368.4 2570.59   388.4 2577.09   398.4 2580.14
   408.5 2582.80   458.5 2594.48   478.6 2599.35   508.6 2607.09   518.6 2609.76
   528.6 2612.65   538.6 2616.24   548.6 2620.12   588.7 2636.15   618.7 2647.73
#Mann= 3 , 0 , 0
       0     0.1       0   100.3   0.045       0   115.3     0.1       0
Bank Sta=   100.3,   115.3
Exp/Cntr=0.3,0.1

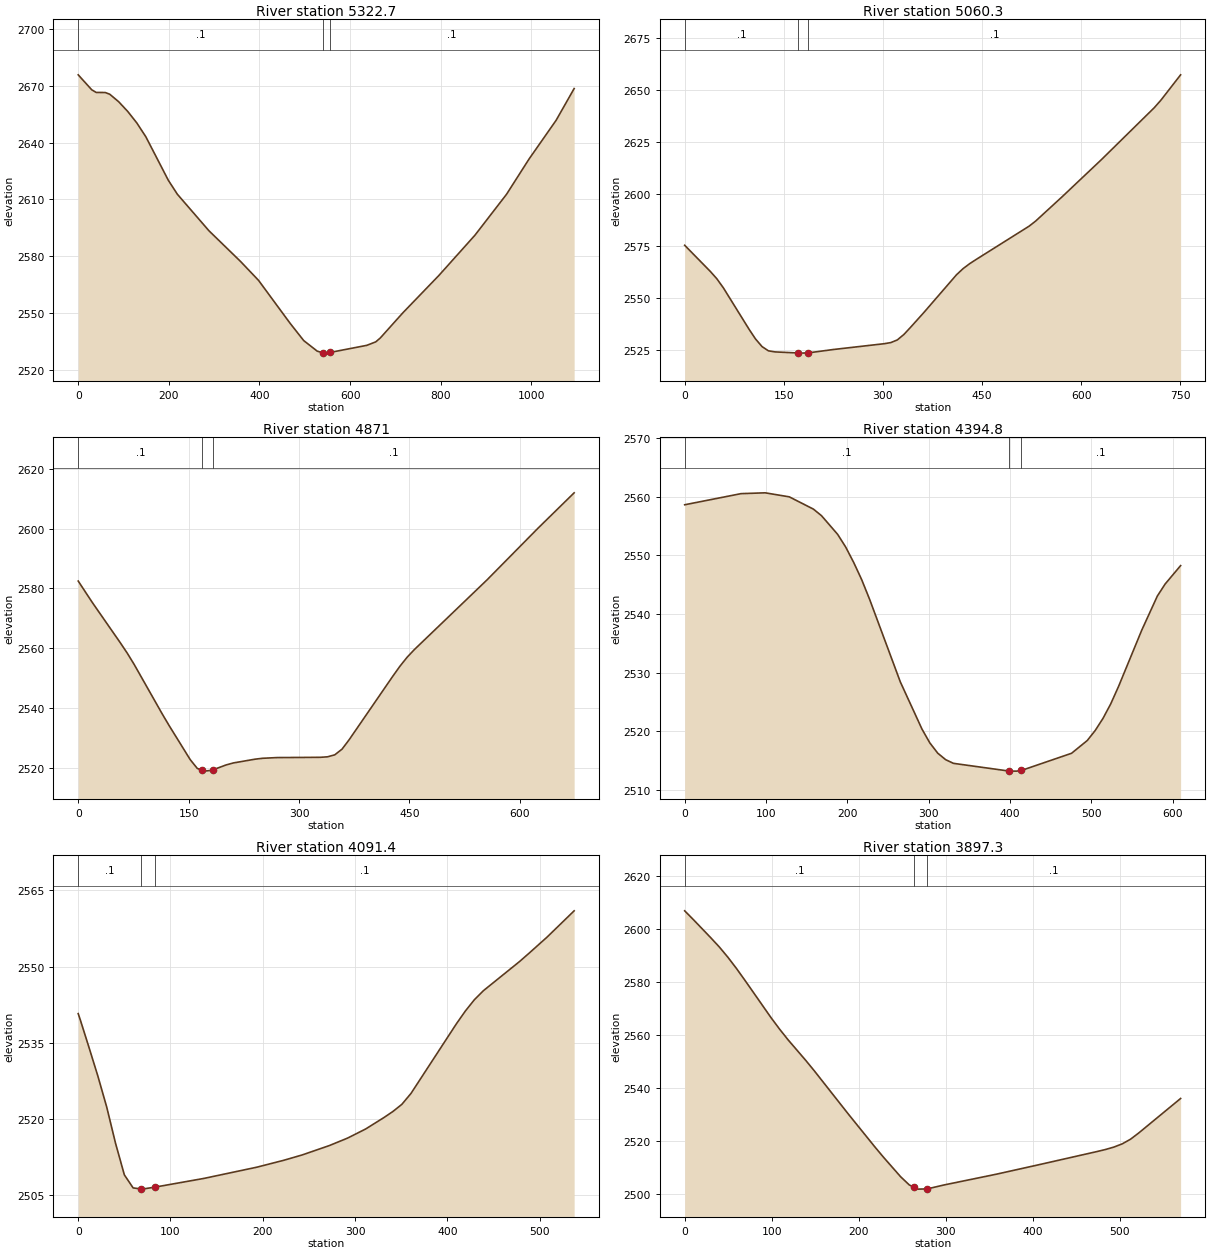
Type RM Length L Ch R = 1 ,5322.7,262.1,262.5,262.9
XS GIS Cut Line= 2
     2010034.031      367638.561     2010446.922      368652.096
#Sta/Elev= 30
       0 2675.86    29.8 2667.96    39.8 2666.55    59.7 2666.51    69.6 2665.61
    89.5 2661.60   109.4 2656.48   129.3 2650.44   149.2 2643.15   199.0 2620.08
   218.9 2612.74   288.5 2593.47   358.2 2577.26   398.0 2567.24   467.6 2544.57
   497.5 2535.47   527.3 2529.88   541.2 2528.85   547.2 2528.81   556.2 2529.19
   636.8 2532.92   656.6 2534.76   666.6 2536.81   716.3 2550.08   795.9 2569.84
   875.5 2591.12   945.2 2612.74   994.9 2631.38  1054.6 2651.83  1094.4 2668.61
#Mann= 3 , 0 , 0
       0     0.1       0   541.2   0.045       0   556.2     0.1       0
Bank Sta=   541.2,   556.2
Exp/Cntr=0.3,0.1

Type RM Length L Ch R = 1 ,5060.3,193.8,189.1,183.7
XS GIS Cut Line= 3
     2009926.420      368058.371     2010042.438      368358.418
     2010287.318      368710.311
#Sta/Elev= 30
       0 2575.53    39.0 2562.89    48.7 2559.41    58.5 2555.08    97.5 2535.11
   107.2 2530.48   117.0 2526.83   126.7 2524.77   136.5 2524.26   171.6 2523.74
   175.5 2523.67   186.6 2523.77   224.2 2525.38   302.2 2528.21   312.0 2528.75
   321.7 2530.01   331.7 2532.64   341.6 2536.02   361.6 2543.08   411.4 2561.38
   421.4 2564.33   431.4 2566.72   441.3 2568.76   521.1 2584.70   531.1 2587.18
   571.0 2598.81   630.8 2616.78   710.5 2641.66   720.5 2645.26   750.4 2657.48
#Mann= 3 , 0 , 0
       0     0.1       0   171.6   0.045       0   186.6     0.1       0
Bank Sta=   171.6,   186.6
Exp/Cntr=0.3,0.1

Type RM Length L Ch R = 1 ,4871,478.2,476.3,474.3
XS GIS Cut Line= 4
     2009723.916      368135.938     2009805.612      368275.564
     2009911.963      368429.201     2010109.993      368687.241
#Sta/Elev= 30
       0 2582.45    19.0 2575.34    57.1 2561.84    66.6 2558.35    76.1 2554.53
   114.2 2537.99   123.7 2534.04   152.2 2522.72   161.8 2519.78   168.7 2519.14
   171.6 2518.87   181.4 2519.15   183.7 2519.36   201.1 2520.95   210.9 2521.61
   240.4 2522.87   250.3 2523.16   270.0 2523.40   329.0 2523.49   338.8 2523.66
   348.6 2524.32   358.5 2526.22   368.3 2529.42   427.5 2550.62   437.3 2554.00
   447.2 2557.04   457.0 2559.58   555.6 2582.86   624.6 2600.08   673.9 2611.96
#Mann= 3 , 0 , 0
       0     0.1       0   168.7   0.045       0   183.7     0.1       0
Bank Sta=   168.7,   183.7
Exp/Cntr=0.3,0.1

Type RM Length L Ch R = 1 ,4394.8,322.4,303.2,284.5
XS GIS Cut Line= 5
     2009297.612      368199.809     2009464.062      368382.944
     2009468.431      368427.073     2009587.261      368603.833
     2009664.501      368675.131
#Sta/Elev= 30
       0 2558.66    69.3 2560.56    99.0 2560.70   128.7 2560.01   158.4 2557.91
   168.3 2556.79   188.1 2553.61   198.0 2551.44   207.9 2548.79   217.8 2545.83
   227.7 2542.41   265.2 2528.40   291.8 2520.35   301.5 2517.98   311.2 2516.23
   320.9 2515.12   330.5 2514.49     399 2513.17   408.0 2513.16     414 2513.27
   475.8 2516.21   495.1 2518.39   504.8 2520.09   514.4 2522.16   523.9 2524.63
   533.5 2527.60   562.2 2537.27   581.3 2543.07   590.8 2545.11   609.9 2548.27
#Mann= 3 , 0 , 0
       0     0.1       0     399   0.045       0     414     0.1       0
Bank Sta=     399,     414
Exp/Cntr=0.3,0.1

Type RM Length L Ch R = 1 ,4091.4,199.7,194,188.3
XS GIS Cut Line= 4
     2009210.769      368630.298     2009212.953      368630.163
     2009394.338      368638.461     2009730.390      368748.478
#Sta/Elev= 30
       0 2540.74     2.2 2539.55    11.7 2534.08    21.3 2528.45    30.9 2522.34
    40.4 2515.25    50.0 2509.00    59.5 2506.43    68.1 2506.22    69.1 2506.19
    83.1 2506.58   136.0 2508.29   193.6 2510.51   223.0 2511.88   242.7 2512.92
   272.2 2514.77   291.8 2516.23   311.4 2518.02   331.1 2520.26   340.9 2521.46
   350.7 2522.88   360.6 2525.03   409.7 2538.71   419.5 2541.25   429.3 2543.48
   439.1 2545.26   478.4 2551.02   488.2 2552.58   507.9 2555.78   537.4 2560.98
#Mann= 3 , 0 , 0
       0     0.1       0    68.1   0.045       0    83.1     0.1       0
Bank Sta=    68.1,    83.1
Exp/Cntr=0.3,0.1

Type RM Length L Ch R = 1 ,3897.3,333.4,337.1,341.3
XS GIS Cut Line= 4
     2009061.049      368868.564     2009247.161      368837.756
     2009451.283      368794.173     2009622.962      368773.885
#Sta/Elev= 30
       0 2606.69     9.9 2603.41    29.8 2596.60    39.7 2593.10    49.6 2589.21
    59.6 2584.91    69.5 2580.37    99.3 2566.37   109.2 2562.01   119.1 2557.93
   139.0 2550.33   148.9 2546.37   188.6 2529.82   218.5 2517.67   228.4 2513.78
   248.3 2506.34   258.2 2503.26   263.8 2502.37   268.2 2501.67   278.8 2501.75
   298.0 2503.23   357.6 2507.25   407.0 2510.86   474.2 2515.86   483.8 2516.62
   493.4 2517.53   503.0 2518.74   512.6 2520.50   522.2 2522.90   570.2 2535.88
#Mann= 3 , 0 , 0
       0     0.1       0   263.8   0.045       0   278.8     0.1       0
Bank Sta=   263.8,   278.8
Exp/Cntr=0.3,0.1

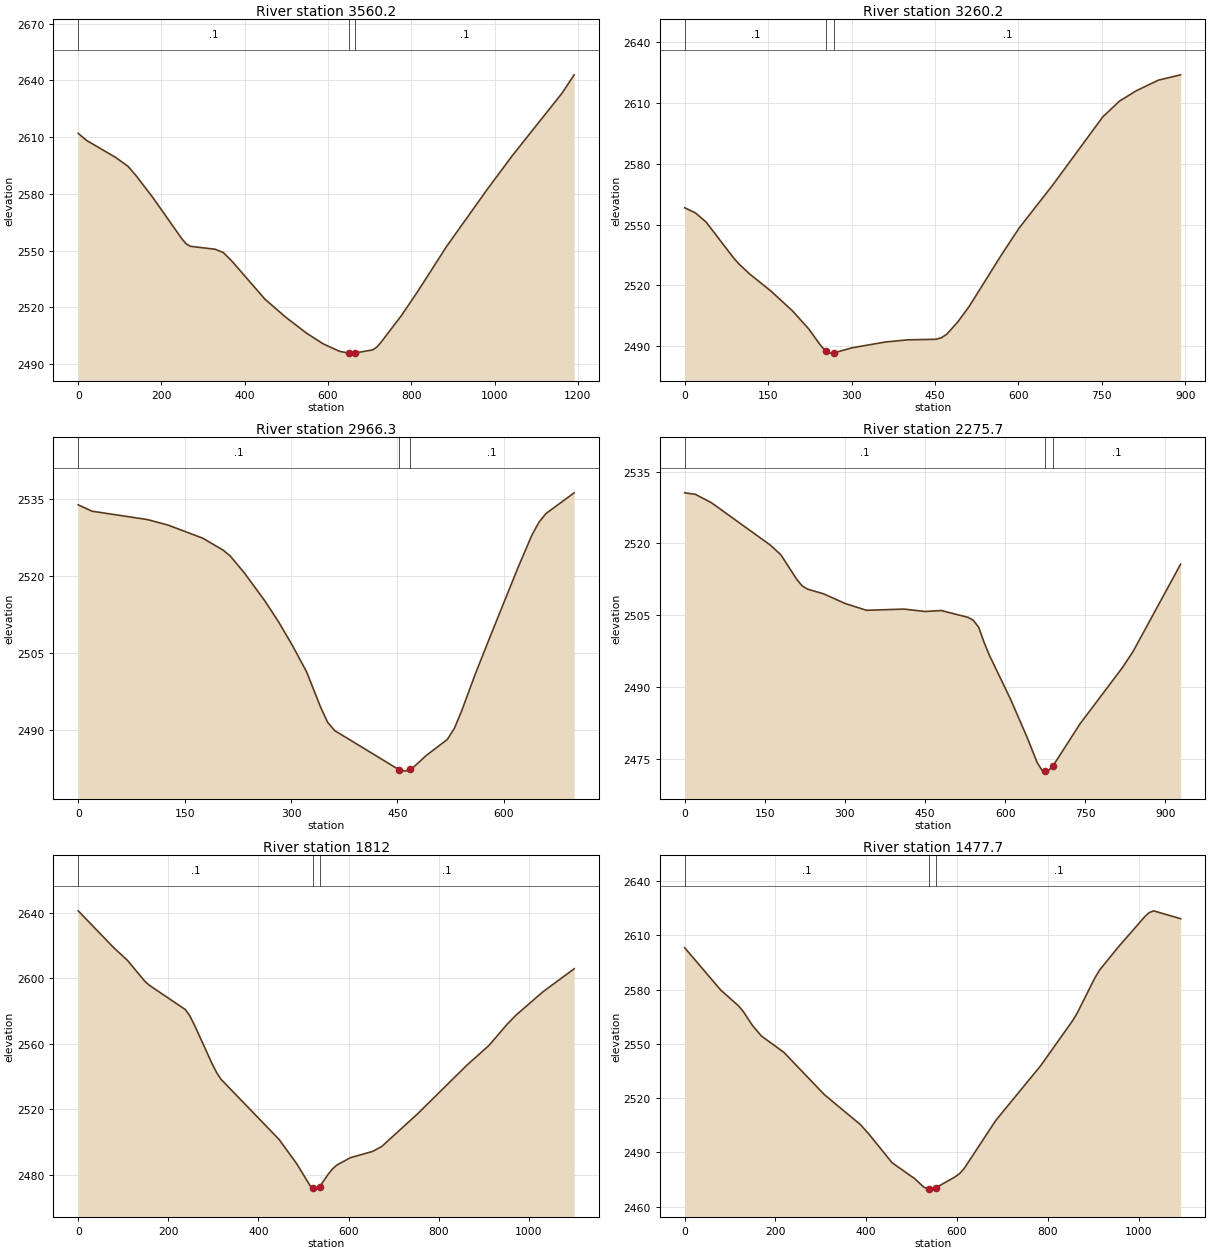
Type RM Length L Ch R = 1 ,3560.2,292.8,299.7,305.4
XS GIS Cut Line= 3
     2008879.898      369138.485     2009535.294      369084.462
     2010067.676      369048.475
#Sta/Elev= 30
       0 2611.97    19.9 2608.26    89.7 2599.26   119.6 2594.54   139.5 2589.47
   179.4 2577.99   249.1 2556.17   259.1 2553.59   269.0 2552.25   328.8 2550.68
   348.7 2548.89   368.7 2544.52   448.4 2524.30   498.2 2514.78   548.0 2506.37
   587.9 2500.71   627.7 2496.69   650.1 2495.75   657.6 2495.74   665.1 2495.82
   707.0 2497.45   716.9 2498.86   726.8 2501.34   776.2 2515.56   815.7 2528.42
   884.9 2552.21   983.7 2582.73  1043.0 2600.26  1161.6 2633.08  1191.2 2642.92
#Mann= 3 , 0 , 0
       0     0.1       0   650.1   0.045       0   665.1     0.1       0
Bank Sta=   650.1,   665.1
Exp/Cntr=0.3,0.1

Type RM Length L Ch R = 1 ,3260.2,293.1,294.2,296.1
XS GIS Cut Line= 3
     2009140.299      369234.553     2009394.114      369297.521
     2010010.617      369427.184
#Sta/Elev= 30
       0 2558.28    19.4 2555.75    38.7 2551.20    87.2 2533.85    96.9 2530.79
   116.2 2525.81   155.0 2517.26   193.7 2507.52   222.8 2498.68   242.1 2491.34
   251.8 2488.06     254 2487.75   261.5 2486.68     269 2486.86   301.5 2489.34
   361.5 2492.19   401.5 2493.23   451.5 2493.50   461.5 2494.24   471.5 2496.07
   491.5 2502.25   511.5 2509.72   571.5 2535.98   601.5 2548.40   661.5 2569.45
   751.5 2603.04   781.5 2610.81   811.5 2615.88   851.5 2621.15   891.5 2623.78
#Mann= 3 , 0 , 0
       0     0.1       0     254   0.045       0     269     0.1       0
Bank Sta=     254,     269
Exp/Cntr=0.3,0.1

Type RM Length L Ch R = 1 ,2966.3,708.3,690.1,671.9
XS GIS Cut Line= 3
     2008929.238      369591.610     2009248.595      369551.505
     2009610.371      369658.619
#Sta/Elev= 30
       0 2533.78    19.5 2532.54    97.5 2530.92   126.8 2529.84   175.6 2527.30
   204.8 2524.94   214.6 2523.80   234.1 2520.59   263.3 2515.10   282.8 2510.99
   302.4 2506.37   321.9 2501.38   341.7 2494.51   351.6 2491.56   361.6 2489.94
   452.8 2482.30   460.9 2482.07   467.8 2482.43   470.8 2482.58   490.7 2485.11
   520.4 2488.22   530.4 2490.40   540.3 2493.66   560.2 2501.06   580.0 2507.93
   619.7 2521.48   639.6 2527.89   649.5 2530.38   659.4 2532.08   699.2 2536.11
#Mann= 3 , 0 , 0
       0     0.1       0   452.8   0.045       0   467.8     0.1       0
Bank Sta=   452.8,   467.8
Exp/Cntr=0.3,0.1

Type RM Length L Ch R = 1 ,2275.7,459.6,463.7,467.8
XS GIS Cut Line= 4
     2009054.010      369931.762     2009578.330      370099.575
     2009805.247      369974.103     2009923.935      369969.017
#Sta/Elev= 30
       0 2530.57    20.0 2530.26    50.0 2528.51   160.2 2519.67   180.2 2517.61
   210.2 2512.44   220.2 2511.11   230.2 2510.44   260.2 2509.47   300.3 2507.46
   340.3 2506.03   410.4 2506.28   450.4 2505.78   480.4 2505.98   530.5 2504.56
   540.5 2503.93   550.5 2502.49   560.5 2499.36   570.5 2496.65   610.4 2487.40
   640.3 2479.71   660.2 2474.17   670.2 2472.43   675.1 2472.43   680.2 2472.43
   690.1 2473.59   740.0 2482.27   819.7 2494.07   839.5 2497.41   928.6 2515.66
#Mann= 3 , 0 , 0
       0     0.1       0   675.1   0.045       0   690.1     0.1       0
Bank Sta=   675.1,   690.1
Exp/Cntr=0.3,0.1

Type RM Length L Ch R = 1 ,1812,335.3,334.3,333.2
XS GIS Cut Line= 3
     2009344.949      370643.699     2009973.106      370430.204
     2010338.568      370190.726
#Sta/Elev= 30
       0 2641.26    79.2 2618.61   108.9 2611.10   148.5 2597.99   158.4 2595.64
   237.6 2580.92   247.6 2577.06   257.5 2571.68   297.1 2547.77   307.0 2542.47
   316.9 2538.26   445.6 2501.53   485.2 2486.50   514.9 2473.04   520.6 2471.93
   524.8 2471.12   535.6 2472.58   554.5 2480.14   564.4 2483.53   574.3 2485.90
   604.0 2490.34   653.5 2494.20   673.4 2497.18   752.8 2517.11   862.0 2546.78
   911.7 2559.04   951.4 2571.83   971.3 2577.46  1030.9 2591.71  1100.4 2605.82
#Mann= 3 , 0 , 0
       0     0.1       0   520.6   0.045       0   535.6     0.1       0
Bank Sta=   520.6,   535.6
Exp/Cntr=0.3,0.1

Type RM Length L Ch R = 1 ,1477.7,452.6,446.2,439.7
XS GIS Cut Line= 2
     2009472.599      370977.851     2010490.137      370579.965
#Sta/Elev= 30
       0 2603.23    79.5 2579.80   119.2 2570.94   129.1 2567.95   149.0 2560.35
   168.8 2554.43   218.5 2545.36   307.9 2521.91   387.4 2505.33   407.2 2499.71
   456.9 2484.27   506.6 2475.49   526.4 2470.89   536.4 2469.67     539 2469.69
     554 2470.53   595.9 2476.47   605.9 2478.32   615.8 2481.12   685.3 2507.65
   784.7 2538.09   854.2 2562.70   864.1 2566.76   903.8 2586.58   913.8 2590.77
   953.5 2603.10  1013.1 2620.28  1023.0 2622.61  1033.0 2623.65  1092.6 2619.30
#Mann= 3 , 0 , 0
       0     0.1       0     539   0.045       0     554     0.1       0
Bank Sta=     539,     554
Exp/Cntr=0.3,0.1