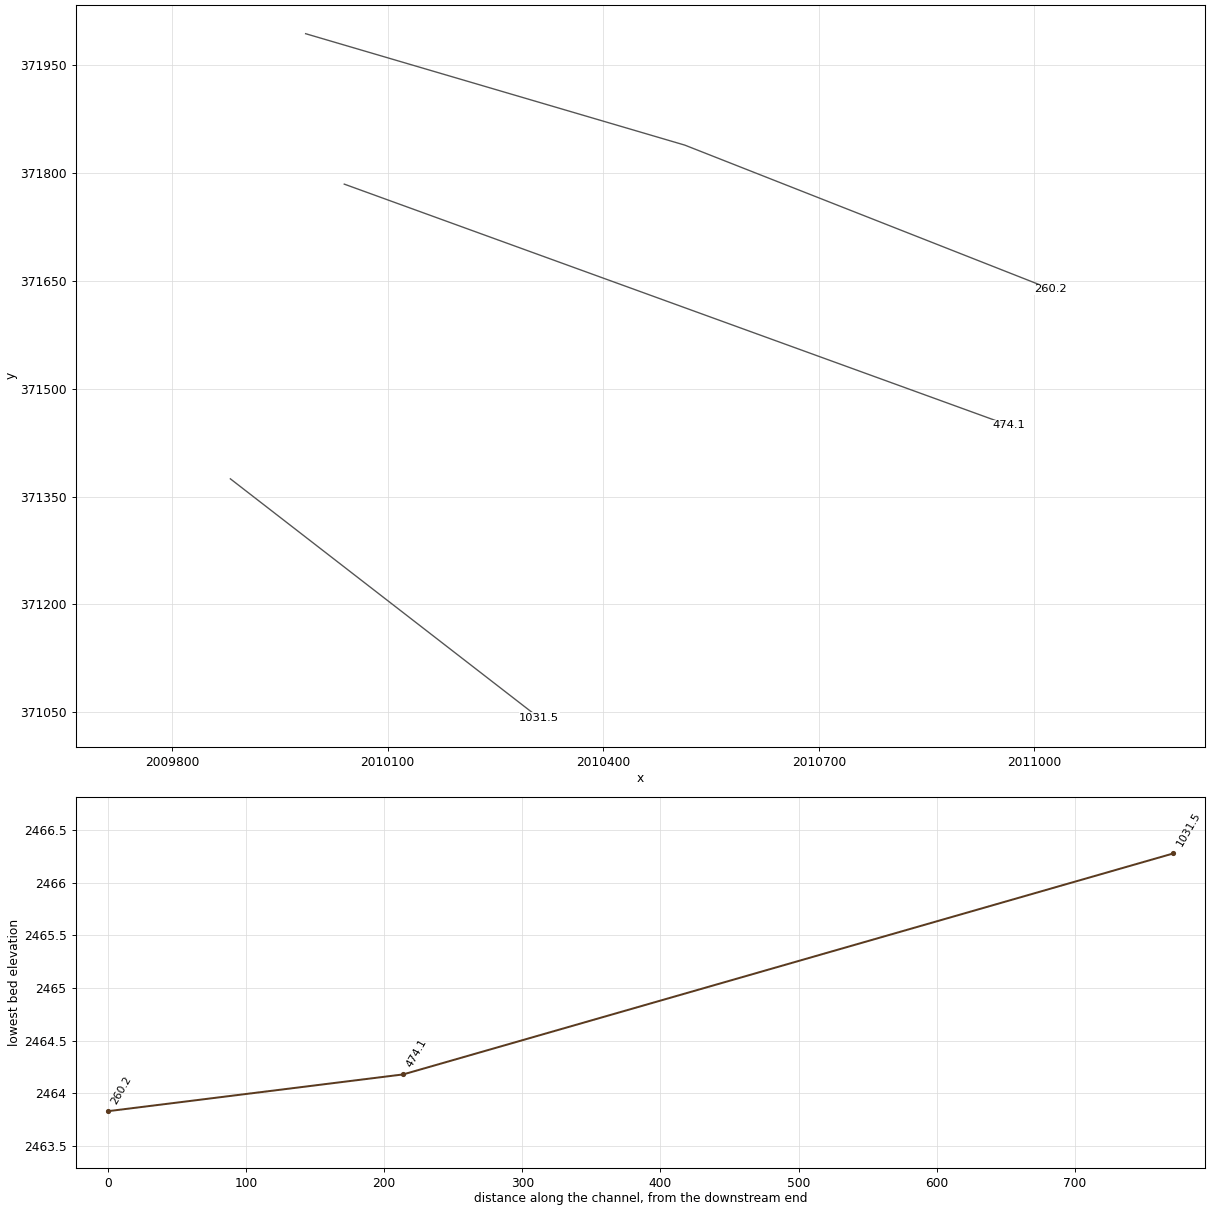
HEC-RAS study NP101.prj: NP101

--- NP101.g01 (geometry) --- (continued)

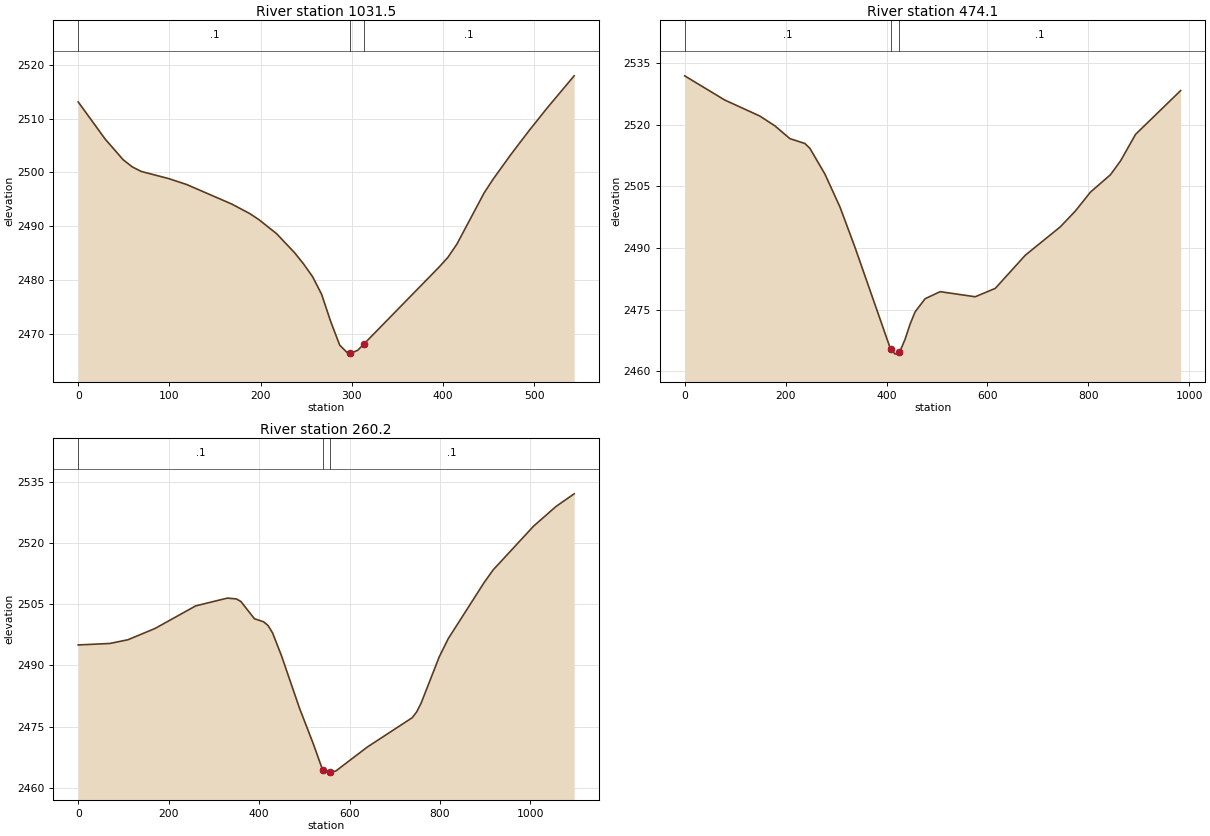
Type RM Length L Ch R = 1 ,1031.5,550.3,557.3,564.4
XS GIS Cut Line= 2
     2009881.418      371374.784     2010311.188      371042.059
#Sta/Elev= 30
       0 2513.08    29.6 2506.17    49.4 2502.33    59.3 2501.02    69.2 2500.17
    98.8 2498.87   118.6 2497.77   168.0 2494.15   187.8 2492.38   197.6 2491.29
   217.4 2488.63   237.2 2485.08   247.0 2483.01   256.9 2480.64   266.8 2477.36
   276.7 2472.33   286.6 2467.94   296.5 2466.28   298.2 2466.40   306.3 2466.99
   313.2 2468.17   395.3 2482.40   405.2 2484.25   415.0 2486.69   444.7 2496.15
   454.6 2498.72   474.3 2503.35   494.1 2507.75   513.9 2511.95   543.5 2517.92
#Mann= 3 , 0 , 0
       0     0.1       0   298.2   0.045       0   313.2     0.1       0
Bank Sta=   298.2,   313.2
Exp/Cntr=0.3,0.1

Type RM Length L Ch R = 1 ,474.1,212.6,213.9,213.3
XS GIS Cut Line= 2
     2010039.859      371784.749     2010963.789      371449.414
#Sta/Elev= 30
       0 2531.95    79.4 2526.06   148.9 2522.16   178.7 2519.78   208.5 2516.66
   238.3 2515.47   248.2 2514.29   278.0 2508.02   307.8 2500.00   337.6 2490.17
   407.1 2465.73   409.8 2465.31   417.0 2464.18   424.8 2464.76   426.9 2464.92
   436.8 2467.79   446.8 2471.50   456.7 2474.48   476.6 2477.68   506.3 2479.39
   575.8 2478.15   615.6 2480.19   675.1 2488.27   744.6 2495.19   774.4 2499.04
   804.2 2503.63   843.9 2507.87   863.8 2511.23   893.6 2517.70   982.9 2528.35
#Mann= 3 , 0 , 0
       0     0.1       0   409.8   0.045       0   424.8     0.1       0
Bank Sta=   409.8,   424.8
Exp/Cntr=0.3,0.1

Type RM Length L Ch R = 1 ,260.2,246.5,260.2,275.8
XS GIS Cut Line= 3
     2009986.102      371994.016     2010513.501      371839.034
     2011022.570      371638.729
#Sta/Elev= 30
       0 2494.98    70.0 2495.34   109.9 2496.25   169.9 2499.01   259.9 2504.55
   329.8 2506.45   349.8 2506.25   359.8 2505.62   389.8 2501.39   409.8 2500.66
   419.8 2499.75   429.8 2497.94   449.8 2492.26   489.7 2479.40   519.7 2470.83
   539.7 2464.62   542.2 2464.43   557.2 2463.83   569.6 2464.09   639.2 2469.96
   738.7 2477.16   748.6 2478.59   758.6 2480.79   798.4 2492.05   818.3 2496.51
   897.8 2510.28   917.7 2513.36  1007.2 2524.09  1057.0 2528.92  1096.8 2531.99
#Mann= 3 , 0 , 0
       0     0.1       0   542.2   0.045       0   557.2     0.1       0
Bank Sta=   542.2,   557.2
Exp/Cntr=0.3,0.1